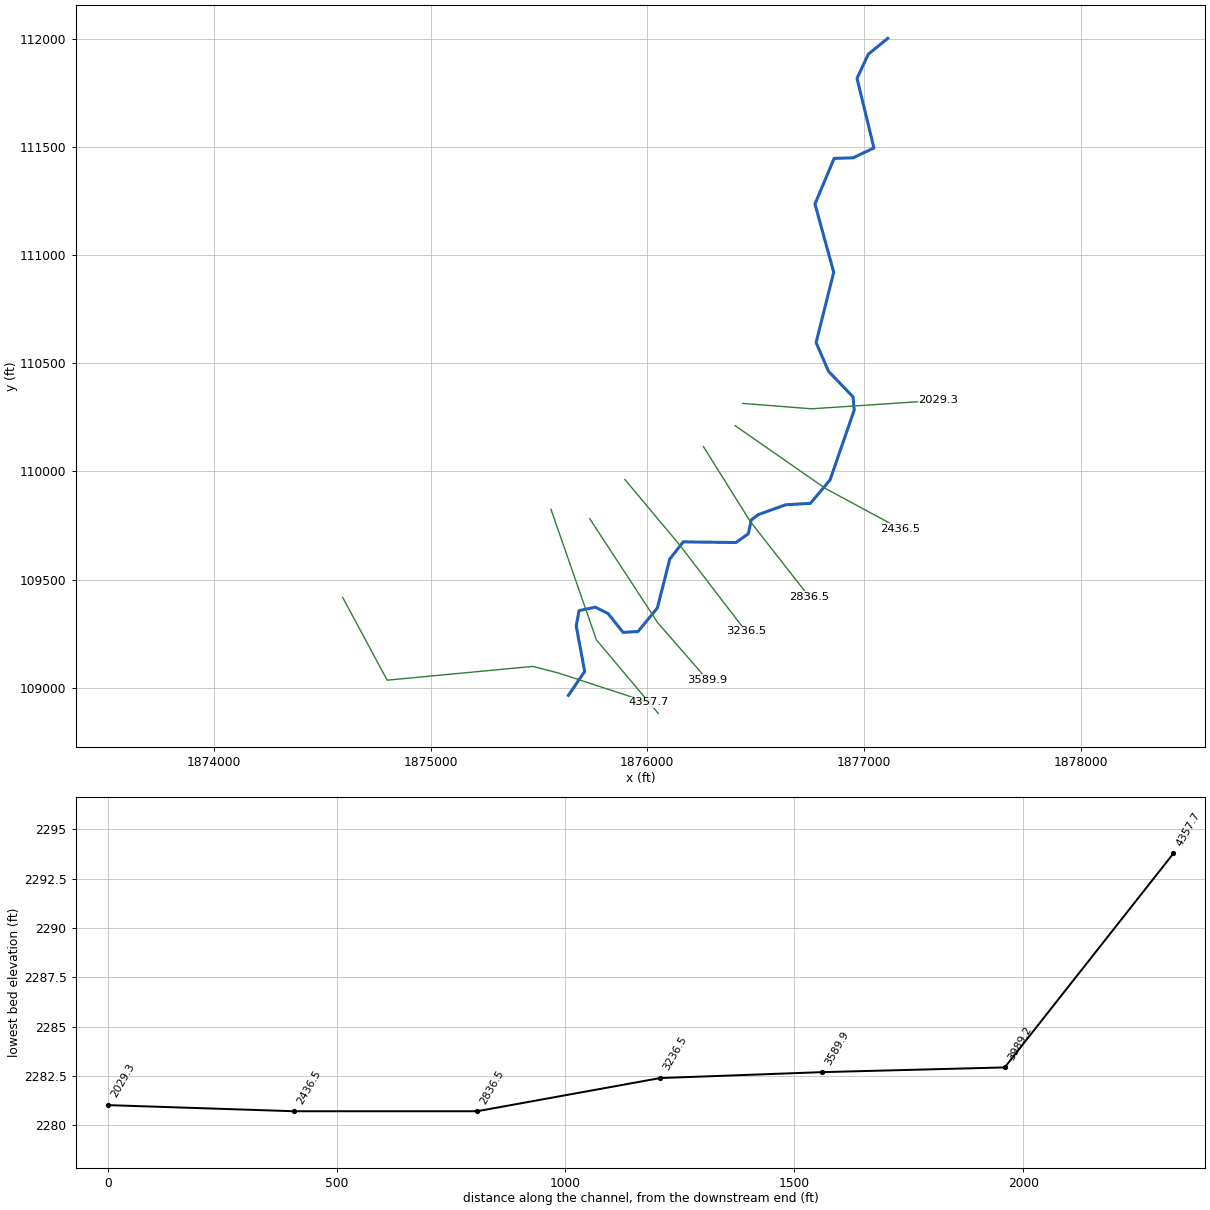
--- NP387.prj (project) ---

Proj Title=NP387
Current Plan=p01
Default Exp/Contr=0,0
English Units
Geom File=g01
Flow File=f01
Plan File=p01
BEGIN DESCRIPTION:
END DESCRIPTION:
DSS Export Rating Curves= 0
DSS Export Rating Curve Sorted= 0
DSS Export Volume Flow Curves= 0
DXF OffsetX= 0
DXF OffsetY= 0
DXF ScaleX= 0
DXF ScaleY= 0

--- NP387.p01 (plan) ---

Plan Title=Floodplain
Program Version=4.00
Geom File=g01
Flow File=f01
K Sum by GR=0
Std Step Tol=0.01
Critical Tol=0.01
Num of Std Step Trials=20
Max Error Tol=0.3
Flow Tol Ratio=0.001
Split Flow NTrial=30
Split Flow Tol=0.02
Split Flow Ratio=0.02
Log Output Level=0
Friction Slope Method=1
Unsteady Friction Slope Method=2
Unsteady Bridges Friction Slope Method=1
Global Log Level=0
CheckData=False
Run HTab=0
Run UNet=0
Run PostProcess=0
UNET Theta=0
UNET Theta Warmup=0
UNET ZTol=0
UNET ZSATol=0
UNET MxIter=0
UNET MaxInSteps=0
UNET DtIC=0
UNET DtMin=0
UNET MaxCRTS=0
UNET WFStab=0
UNET SFStab=0
UNET WFX=0
UNET SFX=0
UNET DSS MLevel=0
UNET DZMax Abort=0
UNET Convert EG Bridges=0
UNET Use Existing IB Tables=0
UNET Froude Limit=0
UNET Froude Power=0
Write IC File=0
Echo Input=False
Echo Output=False
Write Detailed=0

--- NP387.f01 (steady flow) ---

Flow Title=NFF Regression Equation
Program Version=4.10
Number of Profiles= 1
Profile Names=P100yr
River Rch & RM=NP387,Main            ,4357.7
 1679.46
Boundary for River Rch & Prof#=NP387,Main            , 1
Up Type= 0
Dn Type= 3
Dn Slope=0.002607
DSS Import GetInterval= 0
DSS Import GetPeak= 0
DSS Import FillOption= 0

--- NP387.g01 (geometry) ---

Geom Title=USGS 3m DEM
Program Version=4.10

River Reach=NP387           ,Main
Reach XY= 30
      1875635.84      108964.706     1875711.047      109075.047
     1875671.985      109285.984     1875685.262      109356.725
     1875759.915       109372.35     1875818.942      109342.836
     1875888.131      109256.036     1875957.141      109259.943
     1876046.373      109368.878      1876103.37      109594.603
     1876165.662      109674.427     1876408.964      109671.401
     1876466.255      109711.766     1876479.276      109775.568
     1876511.829      109800.307     1876638.275      109845.884
     1876752.533      109852.524     1876842.939      109960.268
     1876954.537       110283.38     1876949.328      110344.578
     1876836.047      110463.068     1876778.755       110595.88
     1876860.167      110920.653     1876773.547      111236.505
     1876862.089      111447.443     1876949.328      111450.047
     1877045.682       111495.62     1876967.558      111817.234
     1877019.641      111929.213      1877109.51      112002.406

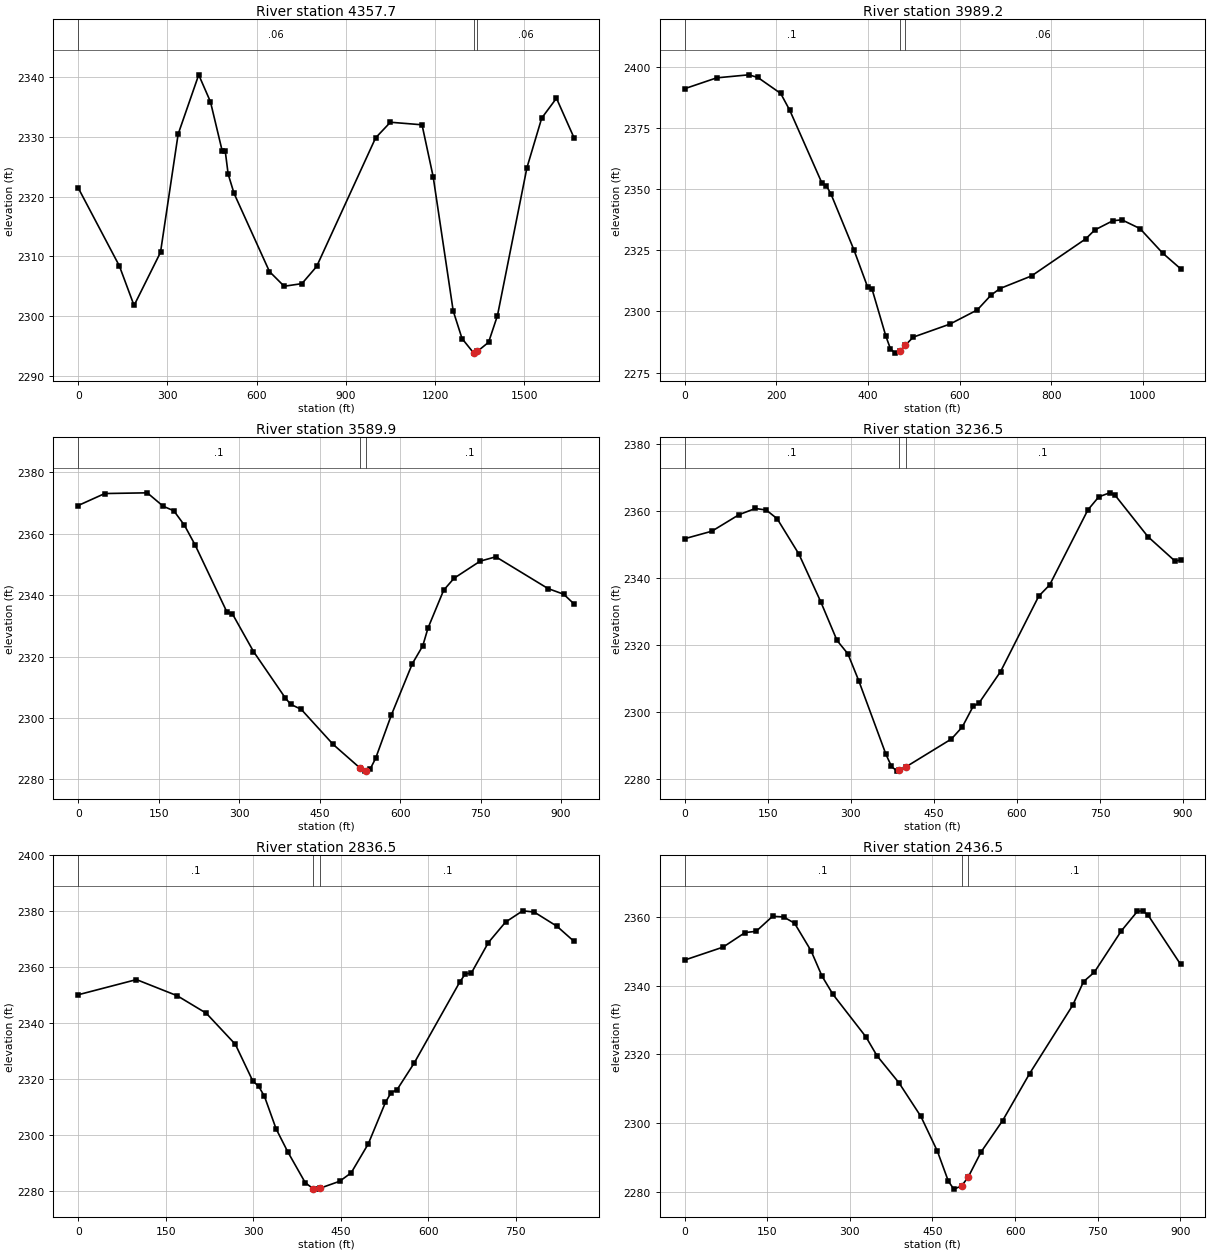
Type RM Length L Ch R = 1 ,4357.7  ,388.3,368.5,348.6
XS GIS Cut Line= 5
     1874594.222      109418.207     1874799.684      109034.997
     1875471.024      109098.607     1875589.169      109068.404
     1876003.905      108932.254
#Sta/Elev= 30
       0 2321.45   138.4 2308.38   187.8 2301.76   276.7 2310.66     336 2330.45
   405.2 2340.39   444.7 2335.87   484.4  2327.6   494.3 2327.64   504.2 2323.76
   524.1 2320.52   643.1 2307.44   692.6 2304.98   752.2 2305.42   801.7 2308.29
  1000.1 2329.84  1049.7 2332.45  1156.1 2332.02  1193.6 2323.31  1260.9 2300.85
  1290.6 2296.22  1329.9 2293.79  1330.3 2293.78  1341.9 2294.06  1379.9  2295.6
  1409.7 2300.06  1508.9 2324.85  1558.5 2333.14  1608.1 2336.47  1667.6  2329.8
#Mann= 3 , 0 , 0
       0     .06       0  1329.9    .045       0  1341.9     .06       0
Bank Sta=1329.9,1341.9
XS Rating Curve= 0 ,0
Exp/Cntr=0.3,0.1

Type RM Length L Ch R = 1 ,3989.2  ,394.3,399.3,404.3
XS GIS Cut Line= 3
     1875555.655      109824.564     1875765.118      109221.312
     1876050.413      108881.487
#Sta/Elev= 30
       0 2391.26    69.8  2395.7   139.7 2396.94   159.6 2395.87   209.5 2389.32
   229.5 2382.35   299.3  2352.7   309.3 2351.46   319.3  2348.1   369.2  2325.3
   399.1 2310.08   409.1 2309.03     439 2289.92     449 2284.72     459 2282.94
   469.5 2283.75   481.5 2286.17   498.9  2289.5   578.7 2294.82   638.6 2300.64
   668.2 2306.64   687.9 2309.38   756.9 2314.56   875.2 2329.74     895 2333.39
   934.4 2337.17   954.1 2337.54   993.6 2333.96  1042.8 2323.97  1082.3 2317.49
#Mann= 3 , 0 , 0
       0      .1       0   469.5    .045       0   481.5     .06       0
Bank Sta=469.5,481.5
XS Rating Curve= 0 ,0
Exp/Cntr=0.3,0.1

Type RM Length L Ch R = 1 ,3589.9  ,350.4,353.3,355.2
XS GIS Cut Line= 3
       1875734.3      109781.821     1876047.892      109300.908
     1876277.656      109036.535
#Sta/Elev= 30
       0 2369.23    49.5 2373.13   128.7 2373.36   158.4 2368.99   178.2 2367.51
     198 2362.79   217.8 2356.41   277.2 2334.53   287.1 2334.03   326.7 2321.67
     386 2306.54     396 2304.47   415.7 2302.82   475.1 2291.41     525 2283.75
   534.5  2282.7     537 2282.89   544.4 2283.44   554.3 2286.84   583.8 2301.03
   622.8 2317.71   642.2  2323.5     652 2329.31   681.2 2341.65   700.6 2345.54
   749.2  2351.1   778.4 2352.52   875.7 2342.17   904.9 2340.33   924.4 2337.13
#Mann= 3 , 0 , 0
       0      .1       0     525    .045       0     537      .1       0
Bank Sta=525,537
XS Rating Curve= 0 ,0
Exp/Cntr=0.3,0.1

Type RM Length L Ch R = 1 ,3236.5  ,403.1,399.8,400.2
XS GIS Cut Line= 3
     1875896.741       109962.55     1876148.657      109660.908
      1876453.98      109261.622
#Sta/Elev= 30
       0 2351.76    49.1    2354    98.2 2358.94   127.7 2360.78   147.4 2360.31
     167 2357.72   206.3 2347.16   245.6 2332.99   275.1  2321.4   294.8 2317.39
   314.4 2309.36   363.5 2287.39   373.4 2283.83   383.2  2282.4     387 2282.76
     399 2283.61   481.7 2291.99   501.4  2295.6   521.1  2301.8     531 2302.59
   570.4 2312.09   639.4 2334.62   659.1 2337.97   728.1 2360.35   747.8 2364.25
   767.5 2365.45   777.4  2364.7   836.5 2352.38   885.8 2345.03   895.6 2345.44
#Mann= 3 , 0 , 0
       0      .1       0     387    .045       0     399      .1       0
Bank Sta=387,399
XS Rating Curve= 0 ,0
Exp/Cntr=0.3,0.1

Type RM Length L Ch R = 1 ,2836.5  ,390.7,400,408.6
XS GIS Cut Line= 3
     1876258.879      110114.878     1876475.489      109767.994
     1876746.854      109420.641
#Sta/Elev= 30
       0  2350.2    99.8 2355.62   169.6 2349.85   219.4  2343.6   269.3 2332.47
   299.2 2319.35   309.2 2317.48   319.2 2313.85   339.1 2302.26   359.1 2294.04
     389 2283.03     403  2280.8     409 2280.72     415 2281.09   448.1 2283.54
   467.7 2286.54   497.1 2296.93   526.5 2311.76   536.3 2315.25   546.1 2316.19
   575.5 2325.72   653.8 2354.75   663.6 2357.74   673.4 2357.87   702.8 2368.85
   732.2 2376.16   761.6  2380.2   781.2 2379.78   820.4 2374.67   849.8 2369.24
#Mann= 3 , 0 , 0
       0      .1       0     403    .045       0     415      .1       0
Bank Sta=403,415
XS Rating Curve= 0 ,0
Exp/Cntr=0.3,0.1

Type RM Length L Ch R = 1 ,2436.5  ,392.7,406.9,419
XS GIS Cut Line= 3
     1876405.491      110211.478     1876822.939      109920.601
     1877167.647      109734.382
#Sta/Elev= 30
       0 2347.54    69.8 2351.32   109.7 2355.56   129.7 2355.92   159.6  2360.3
   179.6 2360.12   199.5 2358.29   229.5 2350.24   249.4 2342.84   269.4  2337.5
   329.2 2325.12   349.2 2319.63   389.1 2311.74     429 2301.91   458.9 2291.79
   478.9    2283   488.8 2280.72   502.8 2281.64   514.8 2284.21   538.2 2291.55
   577.4 2300.71   626.3 2314.41   704.7 2334.38   724.3 2341.24   743.9 2343.99
   792.8 2356.02   822.2 2361.77     832  2361.9   841.8 2360.57   900.6 2346.27
#Mann= 3 , 0 , 0
       0      .1       0   502.8    .045       0   514.8      .1       0
Bank Sta=502.8,514.8
XS Rating Curve= 0 ,0
Exp/Cntr=0.3,0.1

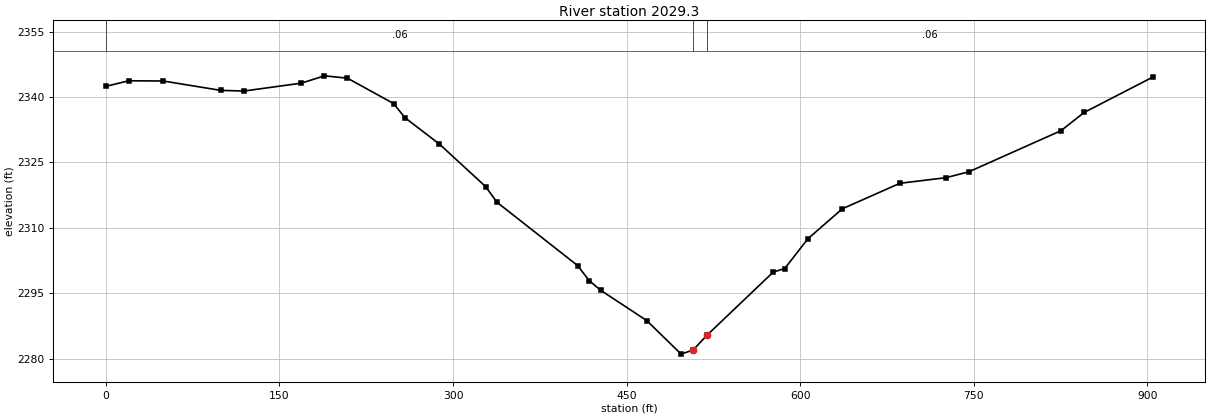
Type RM Length L Ch R = 1 ,2029.3  ,2050.7,2029.2,2007.4
XS GIS Cut Line= 3
     1876440.797      110314.571      1876757.97      110289.571
     1877343.326      110328.591
#Sta/Elev= 30
       0 2342.45    19.9 2343.74    49.7 2343.68    99.4 2341.53   119.3 2341.38
     169 2343.19   188.9 2344.87   208.8 2344.33   248.6 2338.52   258.5 2335.26
   288.3  2329.2   328.1 2319.48     338 2315.86   407.6 2301.35   417.6 2297.91
   427.5 2295.69   467.3 2288.74   497.1 2281.03   507.5 2281.99   519.5 2285.39
   576.7 2299.86   586.6 2300.66   606.5 2307.47   636.3 2314.36   686.1 2320.22
   725.8  2321.5   745.7 2322.86   825.3 2332.29   845.2 2336.46   904.8 2344.61
#Mann= 3 , 0 , 0
       0     .06       0   507.5    .045       0   519.5     .06       0
Bank Sta=507.5,519.5
XS Rating Curve= 0 ,0
Exp/Cntr=0.3,0.1

Chan Stop Cuts=-1
Use User Specified Reach Order=0
Composite Channel Slope=5